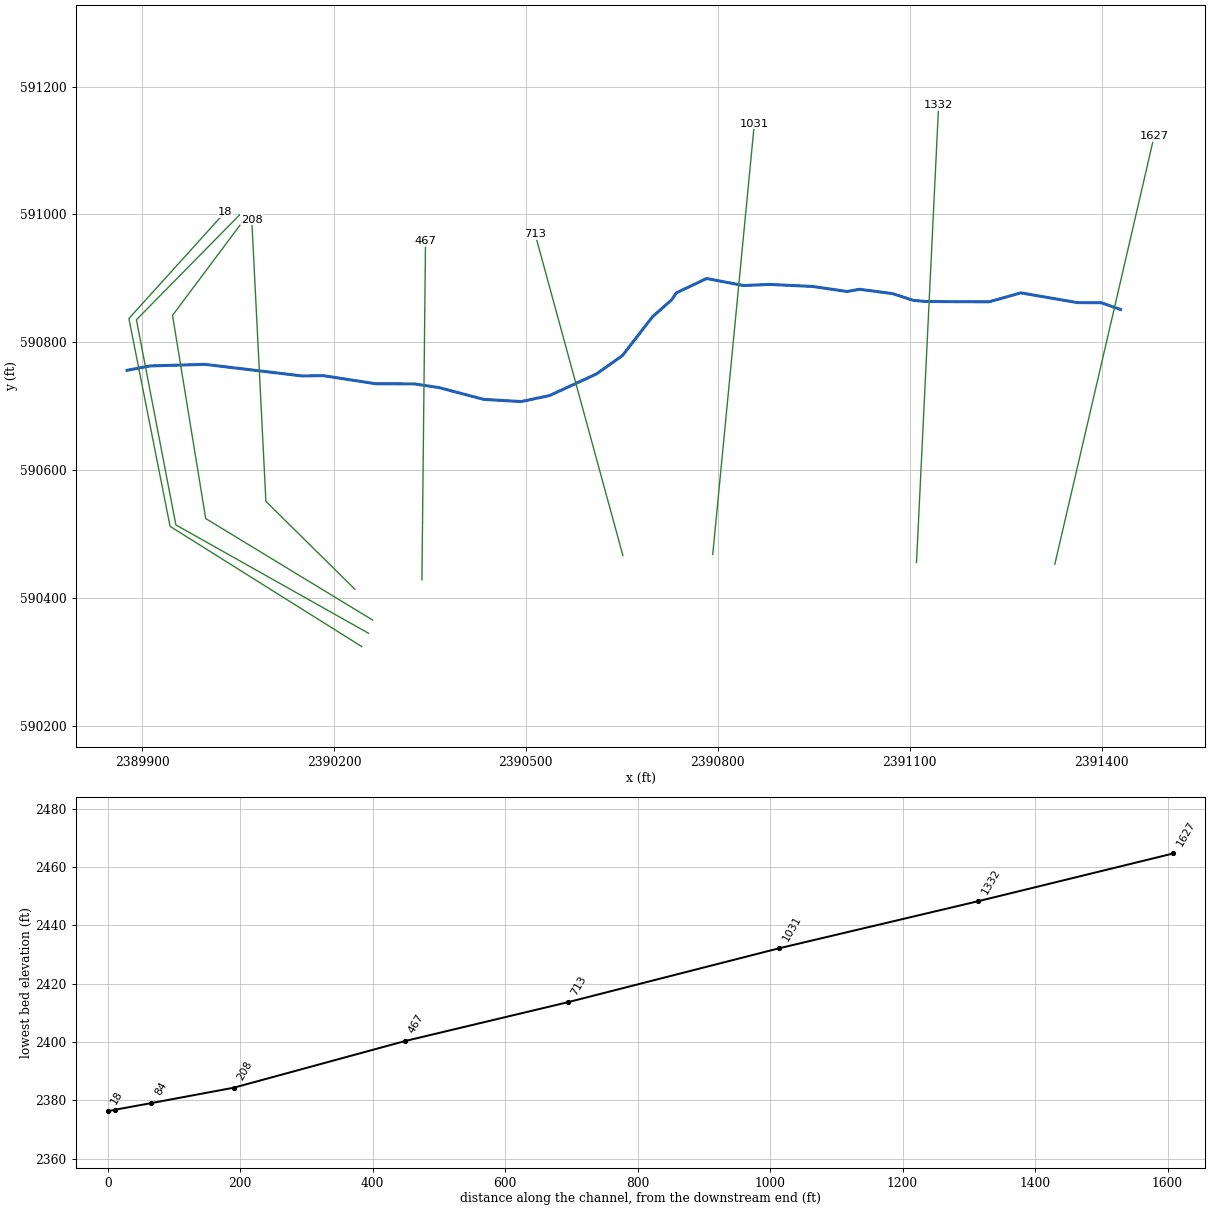
--- DRYRN_T1.prj (project) ---

Proj Title=DRYRN_T1
Current Plan=p01
Default Exp/Contr=0,0
English Units
Geom File=g01
Flow File=f01
Plan File=p01
BEGIN DESCRIPTION:
Stream Name: Dry Run Tributary 1
Flood Zone: Approximate
Pendleton County, West Virginia
HEC-RAS Version: 5.0.7
Hydrology Method:
Regression equation
END DESCRIPTION:
DSS Export Rating Curves= 0
DSS Export Rating Curve Sorted= 0
DSS Export Volume Flow Curves= 0
DXF OffsetX= 0
DXF OffsetY= 0
DXF ScaleX= 0
DXF ScaleY= 0

--- DRYRN_T1.p01 (plan) ---

Plan Title=Floodplain
Program Version=4.00
Geom File=g01
Flow File=f01
K Sum by GR=0
Std Step Tol=0.01
Critical Tol=0.01
Num of Std Step Trials=20
Max Error Tol=0.3
Flow Tol Ratio=0.001
Split Flow NTrial=30
Split Flow Tol=0.02
Split Flow Ratio=0.02
Log Output Level=0
Friction Slope Method=1
Unsteady Friction Slope Method=2
Unsteady Bridges Friction Slope Method=1
Global Log Level=0
CheckData=False
Run HTab=0
Run UNet=0
Run PostProcess=0
UNET Theta=0
UNET Theta Warmup=0
UNET ZTol=0
UNET ZSATol=0
UNET MxIter=0
UNET MaxInSteps=0
UNET DtIC=0
UNET DtMin=0
UNET MaxCRTS=0
UNET WFStab=0
UNET SFStab=0
UNET WFX=0
UNET SFX=0
UNET DSS MLevel=0
UNET DZMax Abort=0
UNET Convert EG Bridges=0
UNET Use Existing IB Tables=0
UNET Froude Limit=0
UNET Froude Power=0
Write IC File=0
Echo Input=False
Echo Output=False
Write Detailed=0

--- DRYRN_T1.f01 (steady flow) ---

Flow Title=Flows
Program Version=5.07
Number of Profiles= 6
Profile Names=P100yr,P10yr,P25yr,P50yr,P500yr,P101yr
River Rch & RM=DRYRN_T1,Main            ,1627
     521     244     344     430     762     634
Boundary for River Rch & Prof#=DRYRN_T1,Main            , 1
Up Type= 0
Dn Type= 3
Dn Slope=0.07406
Boundary for River Rch & Prof#=DRYRN_T1,Main            , 2
Up Type= 0
Dn Type= 3
Dn Slope=0.07406
Boundary for River Rch & Prof#=DRYRN_T1,Main            , 3
Up Type= 0
Dn Type= 3
Dn Slope=0.07406
Boundary for River Rch & Prof#=DRYRN_T1,Main            , 4
Up Type= 0
Dn Type= 3
Dn Slope=0.07406
Boundary for River Rch & Prof#=DRYRN_T1,Main            , 5
Up Type= 0
Dn Type= 3
Dn Slope=0.07406
Boundary for River Rch & Prof#=DRYRN_T1,Main            , 6
Up Type= 0
Dn Type= 3
Dn Slope=0.07406
DSS Import GetInterval= 0
DSS Import GetPeak= 0
DSS Import FillOption= 0

--- DRYRN_T1.g01 (geometry) ---

Geom Title=Geometry
Program Version=5.07

River Reach=DRYRN_T1        ,Main
Reach XY= 30
     2391429.817      590851.444      2391399.09      590862.058
     2391362.283      590862.156     2391273.843       590877.39
     2391224.071       590863.39     2391126.147      590863.888
      2391105.98      590865.645      2391073.17      590876.224
     2391021.672      590883.029     2391002.124      590879.559
      2390948.83      590887.376     2390881.504      590890.626
       2390840.3      590888.874     2390782.614      590899.875
     2390735.235      590877.407     2390727.817      590866.437
     2390697.865       590839.91     2390651.101      590779.475
     2390610.337      590750.603     2390537.099      590716.865
     2390492.764      590707.467     2390434.116      590710.857
     2390364.374      590729.259     2390325.217      590735.135
     2390265.537      590735.254     2390182.866      590748.021
     2390150.323      590747.494      2389998.12      590765.645
     2389912.441      590763.173     2389876.581      590756.309

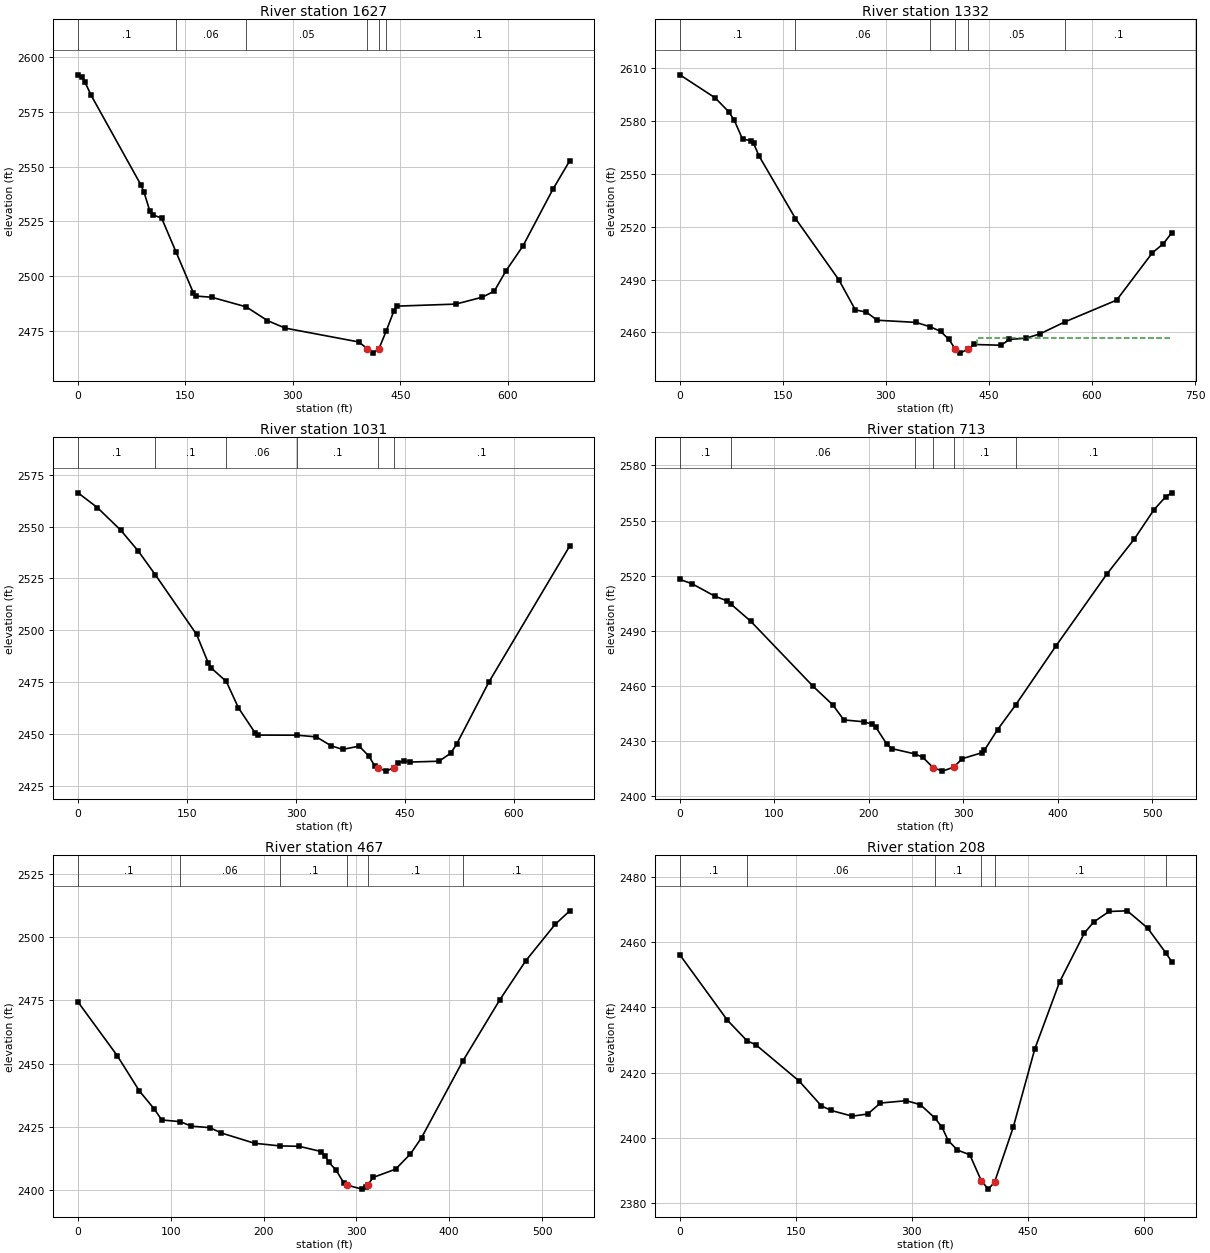
Type RM Length L Ch R = 1 ,1627    ,294.7,294.7,294.7
XS GIS Cut Line= 3
     2391327.017      590453.209     2391420.365      590854.709
 2391482.1741157591121.951345487
#Sta/Elev= 30
       0 2591.96     5.8 2590.76     9.9 2588.52    18.2 2582.67      88 2541.51
    92.1 2538.33   100.3 2529.63   104.4 2527.92   116.7 2526.46  137.022510.812
   161.1 2492.25   164.4  2490.8   186.5 2490.26  234.822485.853   264.4 2479.59
   289.2 2476.14   391.9 2469.81   403.9 2466.71   412.4  2464.7     420 2466.66
  430.422474.914   441.1 2484.15   445.2 2486.19   527.4 2487.12   564.4 2490.28
   581.1 2493.04   597.1 2502.17   621.1  2513.7   662.8 2539.55   686.5 2552.71
#Mann= 6 ,-1 , 0
       0      .1       0  137.02     .06       0  234.82     .05       0
   403.9    .045       0     420     .05       0  430.42      .1       0
Bank Sta=403.9,420
XS Rating Curve= 0 ,0
Exp/Cntr=0.3,0.1

Type RM Length L Ch R = 1 ,1332    ,300.9,300.9,300.9
XS GIS Cut Line= 2
     2391110.733      590455.7892391145.34139723591170.829374136
#Sta/Elev= 30
       0  2605.9    51.2 2592.89    71.2 2584.94    79.2 2580.15    91.2 2569.45
   103.2 2568.67   107.2 2567.13   115.2 2559.96  168.25 2524.52   231.4 2489.81
   255.4  2472.8   271.4 2471.51   287.4 2466.93   343.5 2465.72  364.412463.218
   379.5 2460.64   391.6  2456.1  400.992450.569   407.6 2448.31  419.592450.558
   427.6  2453.2   467.6 2452.78   479.7 2456.07   503.7 2456.78   523.7 2459.13
  560.562466.021   635.8 2478.33   687.9 2505.17   703.9  2510.3   715.9 2516.38
#Mann= 6 ,-1 , 0
       0      .1       0  168.25     .06       0  364.41     .05       0
  400.99    .045       0  419.59     .05       0  560.56      .1       0
#XS Ineff= 2 , 0
                          431.83         2457.03
Permanent Ineff=
       F       F
Bank Sta=400.99,419.59
XS Rating Curve= 0 ,0
Exp/Cntr=0.3,0.1

Type RM Length L Ch R = 1 ,1031    ,318.7,318.7,318.7
XS GIS Cut Line= 2
2390792.16811075590468.4394181952390857.22839723591142.132862589
#Sta/Elev= 30
       0 2566.24    26.6 2559.15    58.7 2548.27    82.8 2538.25  106.39 2526.76
   163.2 2498.02   179.3 2484.22   183.3 2481.84  204.082475.352   220.8 2462.64
   243.6 2450.62   247.6 2449.51  301.77 2449.45     328 2448.64   348.1 2444.39
   364.1 2442.61   386.9 2444.18   400.3 2439.39   408.3 2434.69  412.422433.716
   424.4 2432.14  434.572433.837   440.7 2436.03   448.5 2437.19   456.6 2436.51
   496.8 2436.91   512.8 2440.75   520.9 2445.03   565.3 2474.96   676.8 2540.66
#Mann= 6 ,-1 , 0
       0      .1       0  106.39      .1       0  204.08     .06       0
  301.77      .1       0  412.42    .045       0  434.57      .1       0
Bank Sta=412.42,434.57
XS Rating Curve= 0 ,0
Exp/Cntr=0.3,0.1

Type RM Length L Ch R = 1 ,713     ,245.6,245.6,245.6
XS GIS Cut Line= 2
2390651.68265864590466.6779831492390514.51810361590969.044359328
#Sta/Elev= 30
       0 2517.92    12.7 2515.65    37.5 2508.69    49.8 2506.36    54.52504.323
    74.9 2495.25   141.2 2459.71   161.9 2449.71   173.6 2441.51   195.1 2440.48
   203.4 2439.17   207.5 2437.53   219.2 2428.24   224.1 2425.93  248.752423.025
   257.3 2421.15     268 2415.62     278 2413.65   289.9 2415.79   298.8 2420.37
   319.5 2423.63   322.5 2425.06   336.4 2436.23  355.59  2449.7   398.2 2481.74
   452.2 2520.92   481.2 2539.93   501.9  2555.8   514.4 2562.92520.7553 2565.06
#Mann= 6 ,-1 , 0
       0      .1       0    54.5     .06       0  248.75      .1       0
     268    .045       0   289.9      .1       0  355.59      .1       0
Bank Sta=268,289.9
XS Rating Curve= 0 ,0
Exp/Cntr(USF)=0,0
Exp/Cntr=0.3,0.1

Type RM Length L Ch R = 1 ,467     ,259,259,259
XS GIS Cut Line= 2
2390337.47632978590428.7280920882390343.08923384590958.586235221
#Sta/Elev= 30
       0 2474.36    42.2 2453.16    66.2 2439.12    82.2 2432.03    90.2 2427.69
  110.042427.034   122.1 2425.25   142.2 2424.65   154.2 2422.57   190.2 2418.48
  217.52 2417.43   238.2 2417.28   262.2 2415.19   266.2 2413.55   270.2 2411.01
   278.2  2407.8   286.2 2402.88   290.2 2401.88   306.2 2400.34   310.2    2401
   312.2 2402.06   318.2 2404.99   342.2 2408.24   358.2 2414.26   370.2  2420.7
   414.62450.979   454.6 2475.28   482.3 2490.58     514 2505.01529.8879 2510.41
#Mann= 6 ,-1 , 0
       0      .1       0  110.04     .06       0  217.52      .1       0
   290.2    .045       0   312.2      .1       0   414.6      .1       0
Bank Sta=290.2,312.2
XS Rating Curve= 0 ,0
Exp/Cntr(USF)=0,0
Exp/Cntr=0.3,0.1

Type RM Length L Ch R = 1 ,208     ,124.2,124.2,124.2
XS GIS Cut Line= 3
2390232.63626261590413.9908511922390093.51482261590551.475568365
2390071.41906449590991.754007885
#Sta/Elev= 30
       0 2456.03    61.4 2436.05   86.942429.713    98.3 2428.51   154.5 2417.36
     183 2409.82   195.6 2408.41     223 2406.65   243.1 2407.31   259.5 2410.67
     293 2411.39   311.2 2410.17  329.84 2406.12   339.2 2403.27   347.2 2399.19
   359.2 2396.27   375.2 2394.82   390.2 2386.78   399.3 2384.31   407.3  2386.5
   431.3 2403.19   459.3 2427.24   491.4 2447.76   523.4 2462.67   535.4 2466.09
   555.5 2469.32     579 2469.52   605.3 2464.24  628.642456.706 636.426 2453.98
#Mann= 6 ,-1 , 0
       0      .1       0   86.94     .06       0  329.84      .1       0
   390.2    .045       0   407.3      .1       0  628.64      .1       0
Bank Sta=390.2,407.3
XS Rating Curve= 0 ,0
Exp/Cntr(USF)=0,0
Exp/Cntr=0.3,0.1

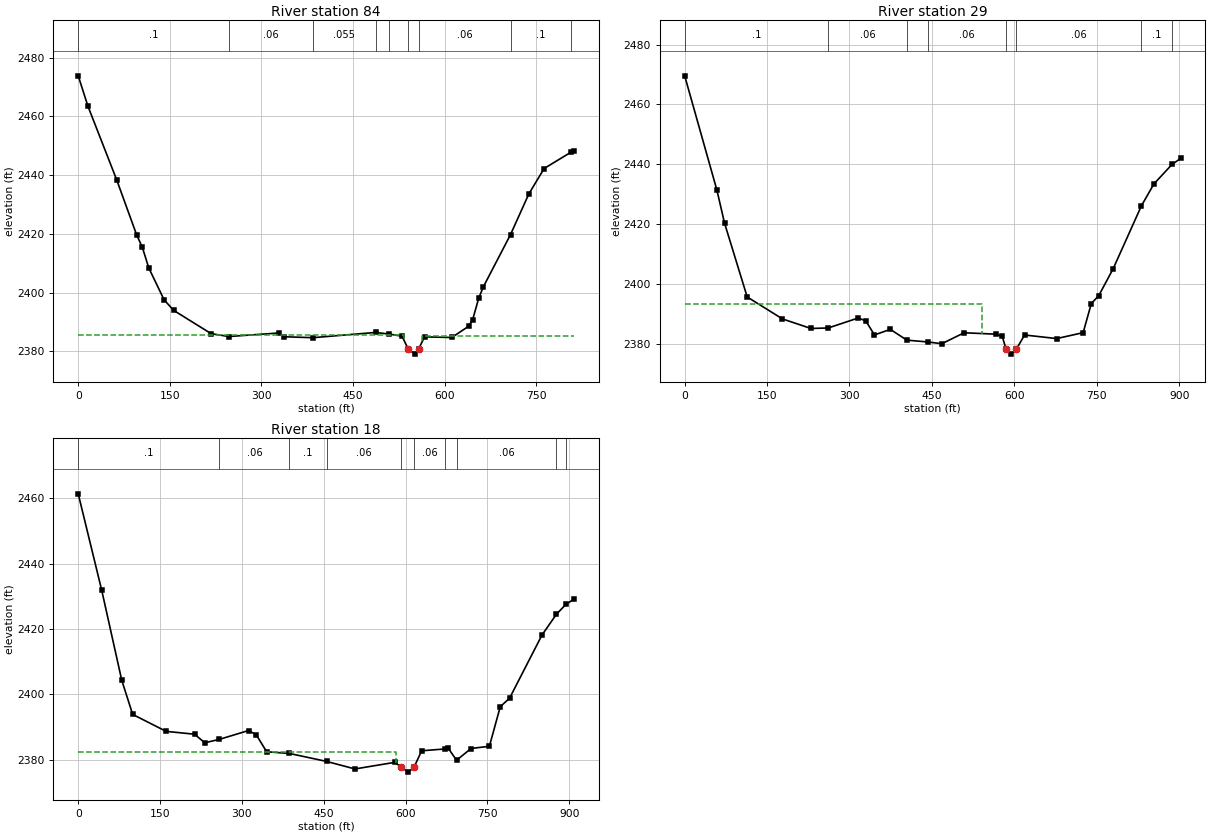
Type RM Length L Ch R = 1 ,84      ,55.1,55.1,55.1
XS GIS Cut Line= 4
2390260.45672714590365.8033015532389999.39943679590524.565415432
2389947.53943883590842.2251081212390058.29194519 590990.26224746
#Sta/Elev= 30
       0 2473.78      16  2463.4    62.9 2438.44    95.6  2419.7     105 2415.42
   115.6 2408.38   140.7 2397.52   156.5 2393.92   217.6 2386.03  246.532385.041
   328.2 2386.24   336.3 2384.97  384.422384.646  487.032386.429  509.562385.873
   530.4 2385.16  540.392380.844   551.1 2379.05  557.492380.787   567.3 2384.93
   611.9 2384.71   639.4 2388.53   646.1  2390.8   655.9 2398.03   663.2 2401.81
  708.072419.735   738.1 2433.59   763.1 2442.23  807.612447.845   812.3 2448.26
#Mann= 9 ,-1 , 0
       0      .1       0  246.53     .06       0  384.42    .055       0
  487.03      .1       0  509.56     .06       0  540.39    .045       0
  557.49     .06       0  708.07      .1       0  807.61      .1       0
#XS Ineff= 2 , 0
             533  2385.4  563.82          2385.2
Permanent Ineff=
       F       F
Bank Sta=540.39,557.49
XS Rating Curve= 0 ,0
Exp/Cntr(USF)=0,0
Exp/Cntr=0.5,0.3

Type RM Length L Ch R = 1 ,29      ,10.7,10.7,10.7
XS GIS Cut Line= 4
2390253.91365931590345.2484926052389952.75665979590514.649304837
  2389891.095018590835.3604732992390052.80542548590999.733614949
#Sta/Elev= 30
       0 2469.56    58.7 2431.41    72.5 2420.47   113.8 2395.81     178 2388.49
   229.7 2385.31  261.282385.473   315.7 2388.79   329.5 2387.87   345.5 2383.15
   374.3 2385.01   404.42381.417  443.192380.792     468 2380.22   508.7 2383.88
   566.1  2383.4     578 2382.67  584.75 2378.55   594.2 2376.75   603.7  2378.4
   618.7 2383.13   677.1 2381.94   725.3 2383.91   740.1  2393.6   753.6 2396.23
     780 2405.26  831.212426.157   854.1 2433.52  887.132440.033   902.7 2441.99
#Mann= 8 ,-1 , 0
       0      .1       0  261.28     .06       0   404.4      .1       0
  443.19     .06       0  584.75    .045       0   603.7     .06       0
  831.21      .1       0  887.13      .1       0
#XS Ineff= 2 , 0
          541.27 2393.58
Permanent Ineff=
       F       F
Bank Sta=584.75,603.7
XS Rating Curve= 0 ,0
Exp/Cntr(USF)=0,0
Exp/Cntr=0.5,0.3

Type RM Length L Ch R = 1 ,18      ,,,
XS GIS Cut Line= 4
2390243.26111709590324.4779210612389943.70537806590512.359516267
2389879.32832162590837.3215893632390029.53633015591003.379932764
#Sta/Elev= 30
       0 2461.31    43.1 2431.81    79.8 2404.32    99.8 2393.89   161.1 2388.71
   213.1 2387.84     232 2385.22  258.452386.255   312.2 2388.97   326.4 2387.63
   345.3 2382.48  387.012381.957  455.352379.514   507.1 2377.22   580.5 2379.25
  591.392377.773   604.9 2376.25  615.192377.697   629.4 2382.77  671.722383.329
   678.3  2383.5  693.322379.873   719.8 2383.47   753.5 2384.16   773.4 2396.26
   790.4 2398.83   849.8 2418.13  876.072424.458  893.632427.516   908.8 2429.15
#Mann= 10 ,-1 , 0
       0      .1       0  258.45     .06       0  387.01      .1       0
  455.35     .06       0  591.39    .045       0  615.19     .06       0
  671.72      .1       0  693.32     .06       0  876.07      .1       0
  893.63      .1       0
#XS Ineff= 2 , 0
          581.84 2382.34
Permanent Ineff=
       F       F
Bank Sta=591.39,615.19
XS Rating Curve= 0 ,0
Exp/Cntr(USF)=0,0
Exp/Cntr=0.5,0.3
LCMann Table=0

Chan Stop Cuts=-1
Use User Specified Reach Order=0
Composite Channel Slope=5